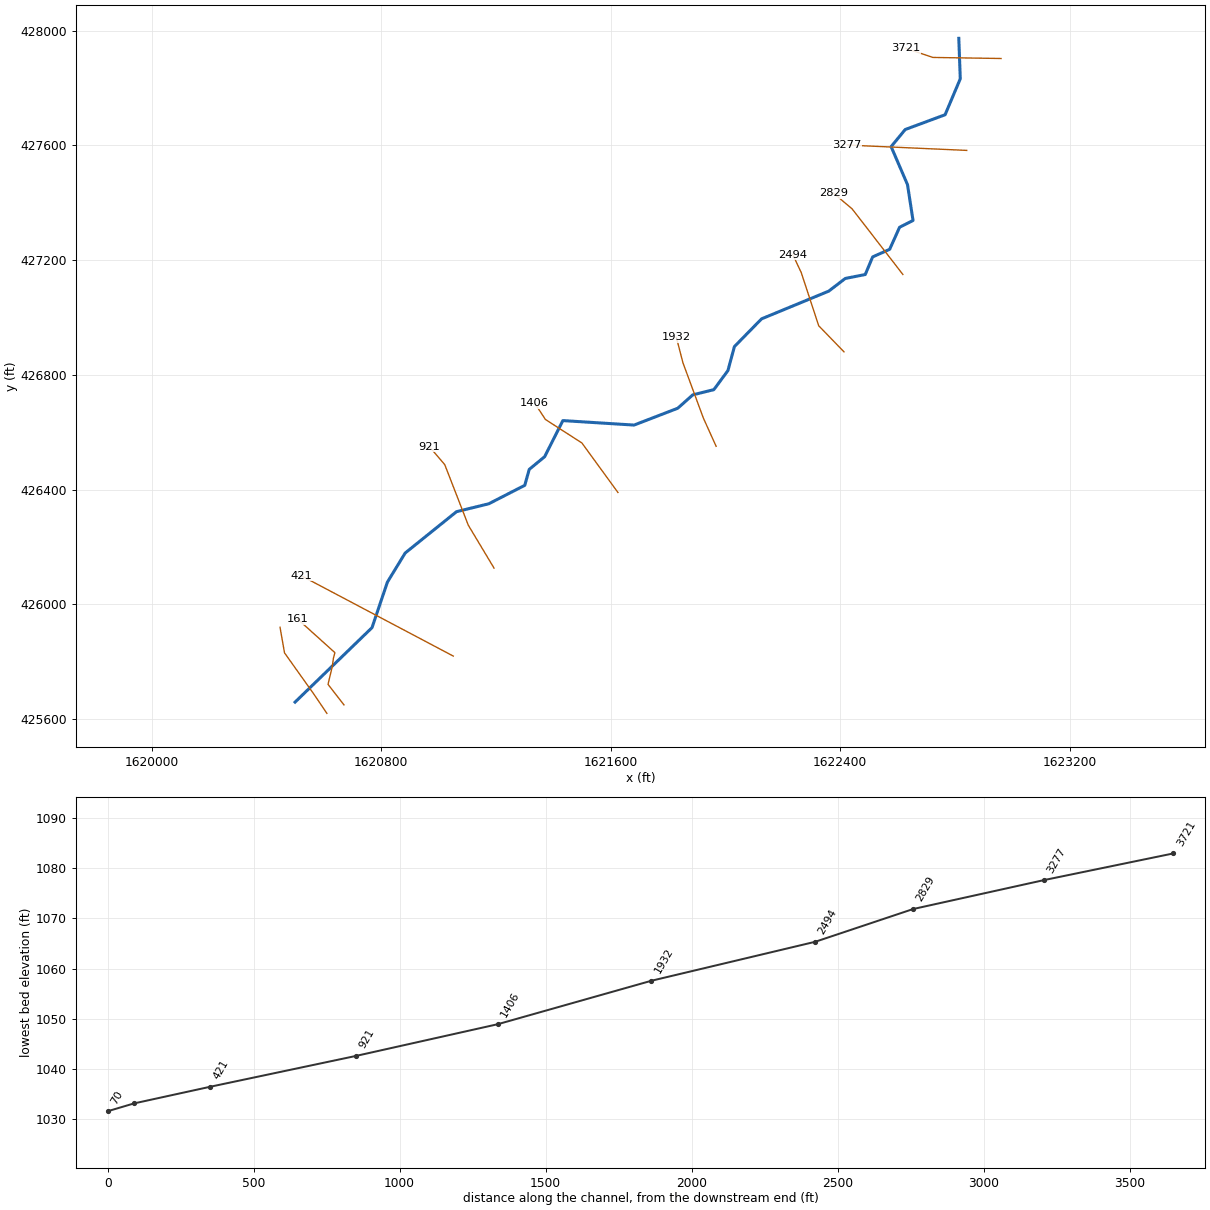
--- HONEYRN1.prj (project) ---

Proj Title=HONEYRN1
Current Plan=p01
Default Exp/Contr=0,0
English Units
Geom File=g01
Flow File=f01
Plan File=p01
BEGIN DESCRIPTION:
---------- MODELED AS PART OF WVEMD CTP PROGRAM, 2023----------
Stream Name: Honey Run
Flood Zone:  AFH
Wetzel County, WV
HEC-RAS Version: RAS 6.3
Vertical Datum: NAVD88
Projection: NAD 1983 StatePlane West Virginia S FIPS 4702 (US Feet)
Terrain: 1-meter West Virginia FEMA R3 South Central (collected 2018-2020)
Land Use: 2019 NLCD
Hydrologic Method:
WV SIR2010-5033 regression equations
Additional Model Notes:
None
END DESCRIPTION:
DSS Export Rating Curves= 0
DSS Export Rating Curve Sorted= 0
DSS Export Volume Flow Curves= 0
DXF OffsetX= 0
DXF OffsetY= 0
DXF ScaleX= 0
DXF ScaleY= 0

--- HONEYRN1.p01 (plan) ---

Plan Title=Floodplain
Program Version=6.30
Short Identifier=Floodplain
Geom File=g01
Flow File=f01
Subcritical Flow
K Sum by GR= 0
Std Step Tol= 0.01
Critical Tol= 0.01
Num of Std Step Trials= 20
Max Error Tol= 0.3
Flow Tol Ratio= 0.001
Split Flow NTrial= 30
Split Flow Tol= 0.02
Split Flow Ratio= 0.02
Log Output Level= 0
Friction Slope Method= 1
Unsteady Friction Slope Method= 2
Unsteady Bridges Friction Slope Method= 1
Parabolic Critical Depth
Global Vel Dist= 0 , 0 , 0
Global Log Level= 0
CheckData=True
Encroach Param=-1 ,0,0, 0
Mapping Interval=1HOUR
Computation Time Step Use Courant=        0
Computation Time Step Use Time Series=    0
Computation Time Step Count To Double=0
Computation Time Step Max Doubling=0
Computation Time Step Max Halving=0
Computation Time Step Residence Courant=0
Run HTab= 0
Run UNet= 0
Run Sediment= 0
Run PostProcess= 0
Run WQNet= 0
Run RASMapper= 0
UNET Theta= 0
UNET Theta Warmup= 0
UNET ZTol= 0
UNET ZSATol= 0
UNET MxIter= 0
UNET Max Iter WO Improvement= 0
UNET MaxInSteps= 0
UNET DtIC= 0
UNET DtMin= 0
UNET MaxCRTS= 0
UNET WFStab= 0
UNET SFStab= 0
UNET WFX= 1
UNET SFX= 1
UNET Gravity=32.17405
UNET 1D Methodology=Finite Difference
UNET DSS MLevel= 1
UNET Pardiso=0
UNET DZMax Abort= 0
UNET Use Existing IB Tables= 0
UNET Froude Reduction=False
UNET Froude Limit= 0
UNET Froude Power= 0
UNET D1 Cores= 0
UNET WindReference=Eulerian
UNET WindDragFormulation=Hsu (1988)
UNET D2 Coriolis=0
UNET D2 Cores= 0
UNET D2 Theta= 1
UNET D2 Theta Warmup= 1
UNET D2 Z Tol= 0.01
UNET D2 Volume Tol= 0.01
UNET D2 Max Iterations= 20
UNET D2 Equation= 0
UNET D2 RampUpFraction=0.1
UNET D2 TimeSlices= 1
UNET D2 Turbulence Formulation=Non-Conservative (original)
UNET D2 Eddy Viscosity=0.3
UNET D2 Transverse Eddy Viscosity=0.1
UNET D2 Smagorinsky Mixing=0
UNET D2 BCVolumeCheck=0
UNET D2 Cores=0
UNET D2 SolverType=PARDISO (Direct)
UNET D2 Minimum Iterations= 3
UNET D2 Maximum Iterations= 30
UNET D2 Restart Number= 10
UNET D2 Relaxation Coeff=1.3
UNET D2 SOR Precondition Iterations= 10
UNET D2 ILUT Maximum Fill= 8
UNET D2 ILUT Tolerance=1E-08
UNET D2 Convergence Tolerance=0.00001
UNET D1D2 MaxIter= 0
UNET D1D2 ZTol=0.01
UNET D1D2 QTol=0.1
UNET D1D2 MinQTol=1
Write IC File= 0
Write IC File at Fixed DateTime=0
Write IC File at Sim End=0
Echo Input=False
Echo Parameters=False
Echo Output=False
Write Detailed= 0
HDF Write Warmup=0
HDF Write Time Slices=0
HDF Flush=0
HDF Compression= 1
HDF Chunk Size= 1
HDF Spatial Parts= 1
HDF Use Max Rows=0
HDF Fixed Rows= 1
Calibration Method= 0
Calibration Iterations= 20
Calibration Max Change=0.05
Calibration Tolerance=0.2
Calibration Maximum=1.5
Calibration Minimum=0.5
Calibration Optimization Method= 1
WQ AD Non Conservative
WQ ULTIMATE=-1
WQ Max Comp Step=1HOUR
WQ Output Interval=15MIN
WQ Output Selected Increments= 0
WQ Output face flow=0
WQ Output face velocity=0
WQ Output face area=0
WQ Output face dispersion=0
WQ Output cell volume=0
WQ Output cell surface area=0
WQ Output cell continuity=0
WQ Output cumulative cell continuity=0
WQ Output face conc=0
WQ Output face dconc_dx=0
WQ Output face courant=0
WQ Output face peclet=0
WQ Output face adv mass=0
WQ Output face disp mass=0
WQ Output cell mass=0
WQ Output cell source sink temp=0
WQ Output nsm pathways=0
WQ Output nsm derived pathways=0
WQ Create Restart=0
WQ Fixed Restart=0
WQ System Summary=0
WQ Write To DSS=0
Sorting and Armoring Iterations= 10
XS Update Threshold= 0.02
Bed Roughness Predictor= 0
Hydraulics Update Threshold= 0.02
Energy Slope Method= 1
Volume Change Method= 1
Sediment Retention Method= 0
Sediment TS Multiplier= 1
Warm Up Method= 0
XS Weighting Method= 0
Number of US Weighted Cross Sections= 1
Number of DS Weighted Cross Sections= 1
Upstream XS Weight=0
Main XS Weight=1
Downstream XS Weight=0
Number of DS XS's Weighted with US Boundary= 1
Upstream Boundary Weight= 1
Weight of XSs Associated with US Boundary= 0
Number of US XS's Weighted with DS Boundary= 1
Downstream Boundary Weight= 0.5
Weight of XSs Associated with DS Boundary= 0.5
Percentile Method= 0
Sediment Output Level= 3
Mass or Volume Output= 0
Output Increment Type= 1
Profile and TS Output Increment= 1
Transport Output Increment 1
XS Output Flag= 0
XS Output Increment= 10
Read HDF5 Sediment Hotstart= 0
Sediment Hotstart Type= 0
Write Gradation File= 0
Read Gradation Hotstart= 0
Write HDF5 File= 1
Write Binary Output= 1
Write DSS Sediment File= 0
DSS Sediment Output Type= 1
SV Curve= 0
Specific Gage Flag= 0
Subcell Erosion Methods= 0
Subcell Deposition Methods= 0
Advection Scheme= 1
Matrix Solver= 0
Implicit Weighting Factor= 1
Maximum Outer Loop Convergence Iterations= 5
Convergence Maximum Absolute= 0.001
Convergence RMSE= 0.0001
Grain Fractions Max Abs Error= 0.001
Max Subgrid Regions= 1
Max Subgrid Length Scale= 3.402823E+38
Initial Layer Thickness= 3.402823E+38
Min Layer Thickness= 3.402823E+38
Max Layer Thickness= 3.402823E+38
Number of Layers= 5

--- HONEYRN1.f01 (steady flow) ---

Flow Title=Flow
Program Version=6.30
Number of Profiles= 1
Profile Names=F01pct
River Rch & RM=HONEYRN1,Main,3721
     561
River Rch & RM=HONEYRN1,Main,1932
     625
Boundary for River Rch & Prof#=HONEYRN1,Main            , 1
Up Type= 0
Dn Type= 3
Dn Slope=0.013
DSS Import GetInterval= 0
DSS Import GetPeak= 0
DSS Import FillOption= 0

--- HONEYRN1.g01 (geometry) ---

Geom Title=Geometry
Program Version=6.30

River Reach=HONEYRN1        ,Main
Reach XY= 30
1622814.07671975427973.487844825 1622819.1935861427832.349708214
1622766.26194289427707.0830000191622627.23775767427655.577655241
1622578.13959034427595.926482275 1622635.2373016427463.511975825
1622654.50457971427338.5722499941622607.56359796 427314.88739644
 1622573.0983198427238.0160526931622513.76745275427211.594039902
1622487.88020664427150.111859873     1622418.406427136.438999996
1622360.69499999 427092.223000021622126.61086775426995.671240345
      1622031.75426898.8230000291622009.26600002426815.312000021
     1621960.169426748.7780000271621886.72287795426730.662570253
1621834.44400001426684.0800000131621682.10500002426625.347000003
     1621433.866426640.9480000141621370.39254996426515.220432743
1621316.51325409426470.7361707091621301.08774823426415.349654451
1621175.53200001426350.9539999961621063.11400001426323.422999993
     1620884.161 426179.343000011620822.21600002426077.937000021
     1620768.531425919.1739999951620500.37350401 425659.60392639

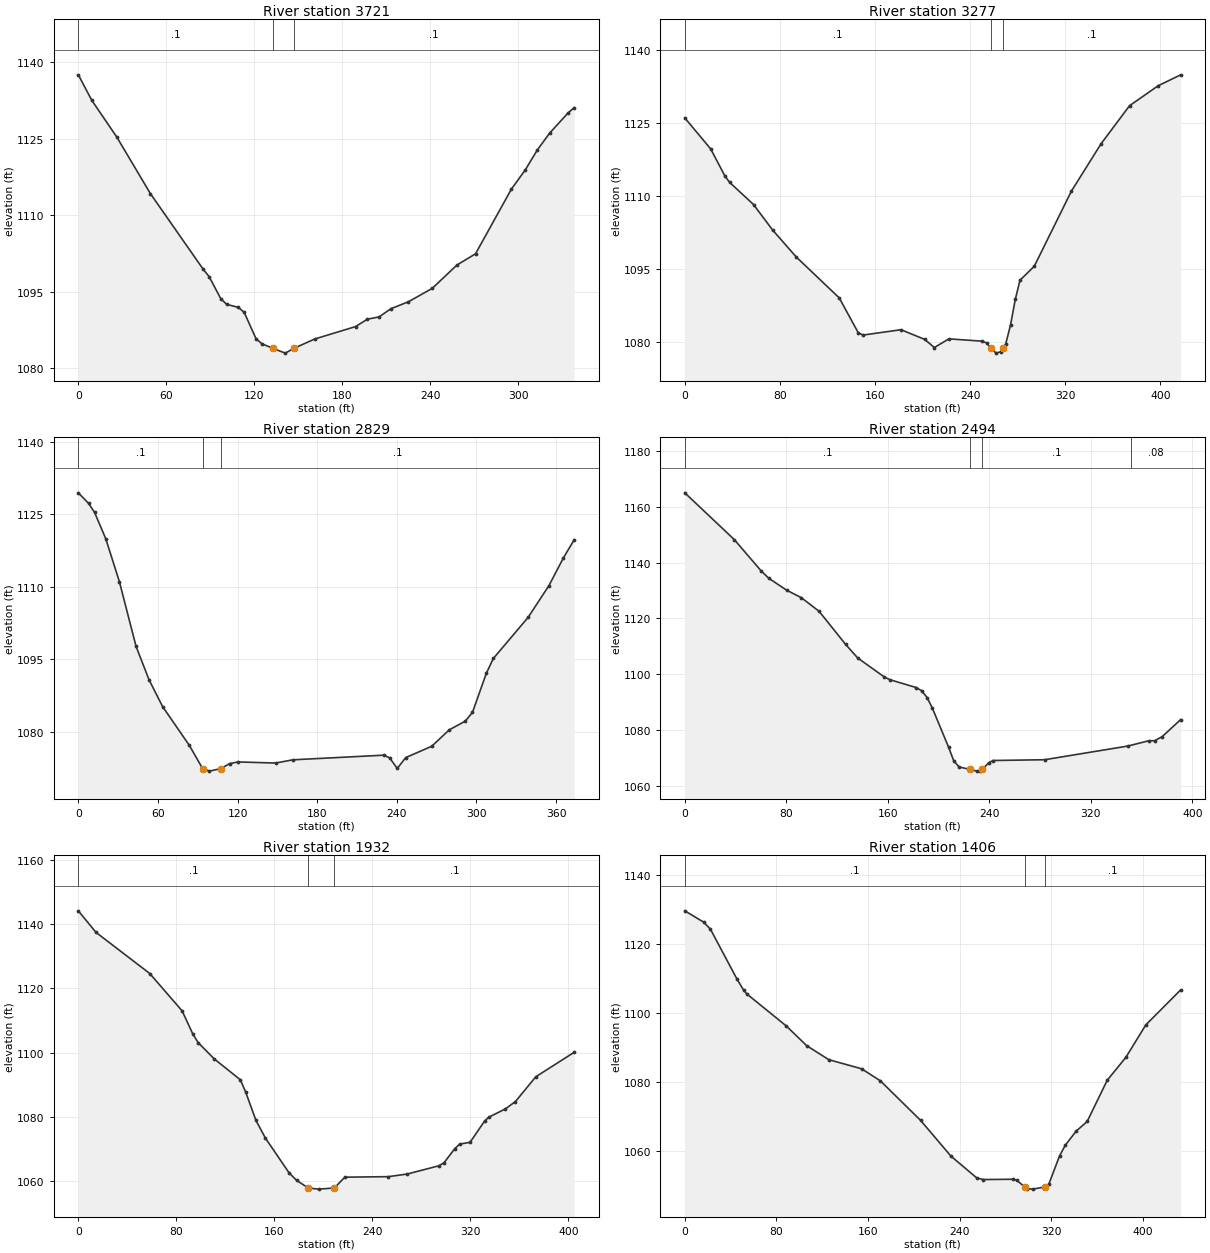
Type RM Length L Ch R = 1 ,3721    ,444.8,444.1,442
XS GIS Cut Line= 3
 1622961.3329269427903.1674568831622723.86229035427906.901271923
1622628.27662532427939.012081268
#Sta/Elev= 30
       0 1137.56     9.2 1132.55    26.2 1125.38    49.2 1114.26    85.2 1099.44
    89.2 1098.02    97.2 1093.67   101.2 1092.56   109.2 1091.97   113.2 1090.98
   121.2 1085.84   125.2 1084.84   132.5 1083.96   141.2    1083  147.11 1083.94
   161.2 1085.76   189.2 1088.21   197.2 1089.65   205.2  1090.1   213.2  1091.7
   225.2 1093.07   241.5  1095.7   258.3 1100.27     271 1102.47   295.4 1115.12
   304.9  1118.9   313.2 1122.84   321.6 1126.14   334.3 1130.14   338.3 1131.11
#Mann= 3 ,-1,0
       0      .1       0   132.5    .045       0  147.11      .1       0
Bank Sta=132.5,147.11
XS Rating Curve= 0 ,0
Exp/Cntr(USF)=0,0
Exp/Cntr=0.3,0.1

Type RM Length L Ch R = 1 ,3277    ,446.7,447.4,435.9
XS GIS Cut Line= 2
1622841.85084561427582.8061264451622425.15708714427601.475201645
#Sta/Elev= 30
       0 1125.98    21.8  1119.6    33.8 1114.02    37.8 1112.72    57.8 1108.19
    73.8 1102.97    93.8  1097.4   129.9 1089.01   145.9 1081.86   149.9 1081.37
   181.9 1082.47   201.9 1080.47   209.9 1078.81   222.2 1080.59     250 1080.12
     254 1079.75   257.51078.612     262 1077.66     266 1077.97   267.8 1078.65
     270 1079.58     274 1083.43     278 1088.68     282 1092.65     294 1095.51
   325.2 1110.93   350.1 1120.64   374.1 1128.48   398.1 1132.57   417.1 1134.83
#Mann= 3 ,-1,0
       0      .1       0   257.5    .045       0   267.8      .1       0
Bank Sta=257.5,267.8
XS Rating Curve= 0 ,0
Exp/Cntr(USF)=0,0
Exp/Cntr=0.3,0.1

Type RM Length L Ch R = 1 ,2829    ,335.5,335.2,331.3
XS GIS Cut Line= 3
1622619.07769236 427150.411725181622442.30501304427378.846842479
1622377.57135582 427433.62147551
#Sta/Elev= 30
       0 1129.42     7.7 1127.24    12.2 1125.39    20.7 1119.91      31    1111
    43.5 1097.67    53.3 1090.76    63.5 1085.23    83.6 1077.23    93.7 1072.39
    98.8 1071.89   107.6 1072.43     114 1073.45   120.5 1073.79   148.6 1073.56
   161.7 1074.23   230.3 1075.19   234.6 1074.62   240.3 1072.45   246.7 1074.69
   266.3 1077.03   279.4 1080.41   291.6 1082.23     297 1084.04   307.4  1092.1
   312.7 1095.18   338.9 1103.67   354.6 1110.24   365.4 1115.92   373.6 1119.71
#Mann= 3 ,-1,0
       0      .1       0    93.7    .045       0   107.6      .1       0
Bank Sta=93.7,107.6
XS Rating Curve= 0 ,0
Exp/Cntr(USF)=0,0
Exp/Cntr=0.3,0.1

Type RM Length L Ch R = 1 ,2494    ,562.5,562.1,557.4
XS GIS Cut Line= 4
 1622413.8769208426880.547197359 1622325.6482543426971.621949874
1622264.93175262427156.6175409181622235.52219712427219.231433272
#Sta/Elev= 30
       0 1164.93      39  1148.2      60 1137.08    66.3 1134.31    80.4 1130.06
    91.8 1127.42   105.8 1122.55   126.8 1110.66   136.2 1105.86   157.2 1099.04
   161.4  1098.1   182.5 1095.23   186.7 1094.08   190.9 1091.69   195.1 1087.88
   207.8 1073.98     212 1068.95   216.2 1066.84   224.6 1065.98   230.2 1065.35
     233 1065.42   234.3 1065.98   239.7 1068.42   242.9 1069.15   283.5 1069.43
   349.1 1074.32   365.6 1076.22   370.2 1076.23   376.2  1077.7   390.7 1083.79
#Mann= 4 ,-1,0
       0      .1       0   224.6    .045       0   234.3      .1       0
  351.51     .08       0
Bank Sta=224.6,234.3
XS Rating Curve= 0 ,0
Exp/Cntr(USF)=0,0
Exp/Cntr=0.3,0.1

Type RM Length L Ch R = 1 ,1932    ,519.7,525.6,529.8
XS GIS Cut Line= 4
 1621968.0804842426551.3981778161621923.49180329426650.062493039
1621852.33965288426842.6476467931621829.57096476426930.876313291
#Sta/Elev= 30
       0 1144.16    14.4 1137.46    58.3 1124.65    84.7 1113.04    93.4 1105.87
    97.8 1103.14   110.9 1098.09   132.2 1091.59   136.5 1087.85     145 1078.91
   152.6 1073.49     172 1062.62   178.2 1060.26   187.7  1057.9   196.2 1057.55
     209 1057.91   217.5 1061.27     253 1061.43   268.5 1062.25   294.3 1064.82
   298.5 1065.76   307.1 1070.07   311.3 1071.59   319.7  1072.1   331.7 1078.79
     335 1079.93   348.6 1082.53   356.8 1084.82   373.4 1092.52   404.7 1100.13
#Mann= 3 ,-1,0
       0      .1       0   187.7    .045       0     209      .1       0
Bank Sta=187.7,209
XS Rating Curve= 0 ,0
Exp/Cntr(USF)=0,0
Exp/Cntr=0.3,0.1

Type RM Length L Ch R = 1 ,1406    ,487.5,485.1,475.9
XS GIS Cut Line= 4
1621625.75458623426390.4491458721621500.24219292426562.921958446
  1621373.022148426644.8892357091621335.45381259426702.095564632
#Sta/Elev= 30
       0 1129.72    16.4 1126.45    22.4 1124.38    45.6 1109.89    51.3 1106.72
    54.2 1105.57    88.6 1096.29   106.5 1090.54   125.8 1086.48   154.4 1083.84
   170.8 1080.35     206 1068.84   232.5 1058.46   255.1 1052.11   260.9 1051.66
   286.9 1051.75   289.8 1051.48   296.81049.562   299.1 1049.02   303.9 1048.88
   314.91049.522   318.1 1050.44   327.4 1058.57   332.4 1061.65   341.8  1065.7
   351.5 1068.55     369 1080.51   385.3 1087.17   402.7 1096.59   433.1 1106.74
#Mann= 3 ,-1,0
       0      .1       0   296.8    .045       0   314.9      .1       0
Bank Sta=296.8,314.9
XS Rating Curve= 0 ,0
Exp/Cntr(USF)=0,0
Exp/Cntr=0.3,0.1

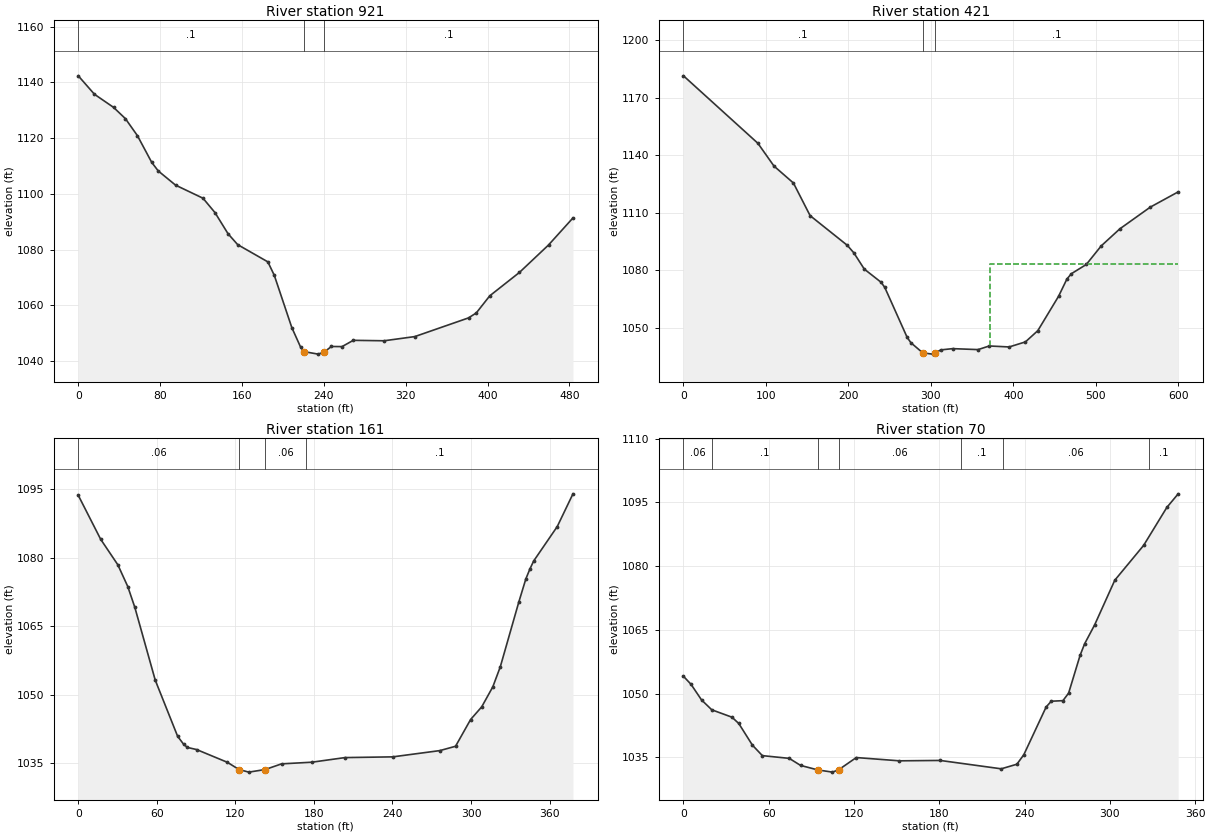
Type RM Length L Ch R = 1 ,921     ,490.4,500.1,504.1
XS GIS Cut Line= 4
 1621193.7818114426126.9728992881621104.13010189426276.392415132
1621022.16282463426487.2873889221620968.37179893426550.470498479
#Sta/Elev= 30
       0 1142.37    15.8 1135.76    34.5 1131.05    46.1    1127    57.8 1120.91
    71.8 1111.32    78.2 1108.24    95.1 1103.16   121.9 1098.47   133.6 1093.32
   146.4 1085.72   155.8 1081.82   185.3 1075.64   191.6  1070.8   208.7 1052.08
   217.3 1045.06   220.7 1043.44   234.5 1042.55   240.5 1043.33   247.4 1045.29
   257.8 1045.25   268.8  1047.5   298.9 1047.34   328.9 1048.84   381.4 1055.54
     389 1057.32   402.2 1063.47   431.2 1071.86   459.6 1081.69   483.5  1091.4
#Mann= 3 ,-1,0
       0      .1       0   220.7    .045       0   240.5      .1       0
Bank Sta=220.7,240.5
XS Rating Curve= 0 ,0
Exp/Cntr(USF)=0,0
Exp/Cntr=0.3,0.1

Type RM Length L Ch R = 1 ,421     ,269.4,260.4,247.6
XS GIS Cut Line= 2
1621051.82018705425820.0466515361620521.63430453426100.313262833
#Sta/Elev= 30
       0 1181.43    90.2 1146.27   109.7  1134.4   133.3 1125.55   153.5 1108.56
   198.5 1093.12   206.5 1089.18   219.2 1080.69   239.5 1073.85     244 1071.17
   271.1 1045.14   275.7 1042.31   290.2 1036.99   302.1 1036.38     305 1036.95
   311.9 1038.58   326.3 1039.24   357.1 1038.74   370.7 1040.63   394.8 1040.12
   414.5 1042.75   429.5 1048.59   454.7 1066.53   464.8 1075.51   470.2 1078.29
   488.3  1083.1   506.4 1092.79     529 1101.68   565.9    1113   599.7 1120.94
#Mann= 3 ,-1,0
       0      .1       0   290.2    .045       0     305      .1       0
#XS Ineff= 2 , 0
                          371.99         1083.31
Permanent Ineff=
       F       F
Bank Sta=290.2,305
XS Rating Curve= 0 ,0
Exp/Cntr(USF)=0,0
Exp/Cntr=0.3,0.1

Type RM Length L Ch R = 1 ,161     ,84.3,90.2,99.7
BEGIN DESCRIPTION:
Low water crossing
END DESCRIPTION:
XS GIS Cut Line= 6
1620670.62534752425650.0461801731620615.20898285425721.475219595
1620629.92436967425783.3359991391620633.89297447 425812.30681416
1620639.19431423425832.0115825781620509.76444458425948.601712326
#Sta/Elev= 30
       0 1093.63    17.1 1084.02    30.2 1078.44    37.8 1073.68    43.2 1069.12
    58.8 1053.18    75.9  1040.9    80.5 1039.15    83.4 1038.46    90.4    1038
   113.9 1035.21  122.811033.625   130.3 1033.06   142.8 1033.63   155.3 1034.87
   178.4 1035.23   203.7 1036.24   240.2  1036.4   276.2 1037.77   288.2 1038.72
   299.7 1044.57   308.2 1047.35   316.7 1051.74   322.4 1056.12   336.5 1070.25
   341.9 1075.34     345 1077.51   347.9 1079.27   365.9  1086.8   377.9 1093.96
#Mann= 4 ,-1,0
       0     .06       0  122.81    .045       0   142.8     .06       0
  174.06      .1       0
Bank Sta=122.81,142.8
XS Rating Curve= 0 ,0
Exp/Cntr(USF)=0,0
Exp/Cntr=0.3,0.1

Type RM Length L Ch R = 1 ,70      ,,,
XS GIS Cut Line= 4
1620611.25882814425620.3197040891620563.56274475425690.720690349
1620463.57444134425831.1361617121620447.90021705425920.452098651
#Sta/Elev= 30
       0 1054.05     5.3 1052.17    12.7 1048.49    19.9 1046.17    34.1 1044.43
    38.9 1042.95    48.5 1037.85    55.5 1035.38    74.4 1034.74    82.4 1033.08
94.49811 1032.02   104.8  1031.5109.10511032.038   121.6 1034.93   151.9 1034.16
   180.6 1034.25   223.6 1032.28   234.6 1033.36   239.5 1035.61   255.2 1046.84
   258.8 1048.19     267 1048.32     271 1050.09   279.1 1059.01   282.3 1061.73
   289.3 1066.14   303.5 1076.67   323.8 1084.87   340.1 1093.79   348.1    1097
#Mann= 7 ,-1,0
       0     .06       0      20      .1       094.49811    .045       0
109.1051     .06       0  195.04      .1       0  225.04     .06       0
  327.41      .1       0
Bank Sta=94.49811,109.1051
XS Rating Curve= 0 ,0
Exp/Cntr(USF)=0,0
Exp/Cntr=0.3,0.1
LCMann Table=0

Chan Stop Cuts=-1
Use User Specified Reach Order=0
Composite Channel Slope=5